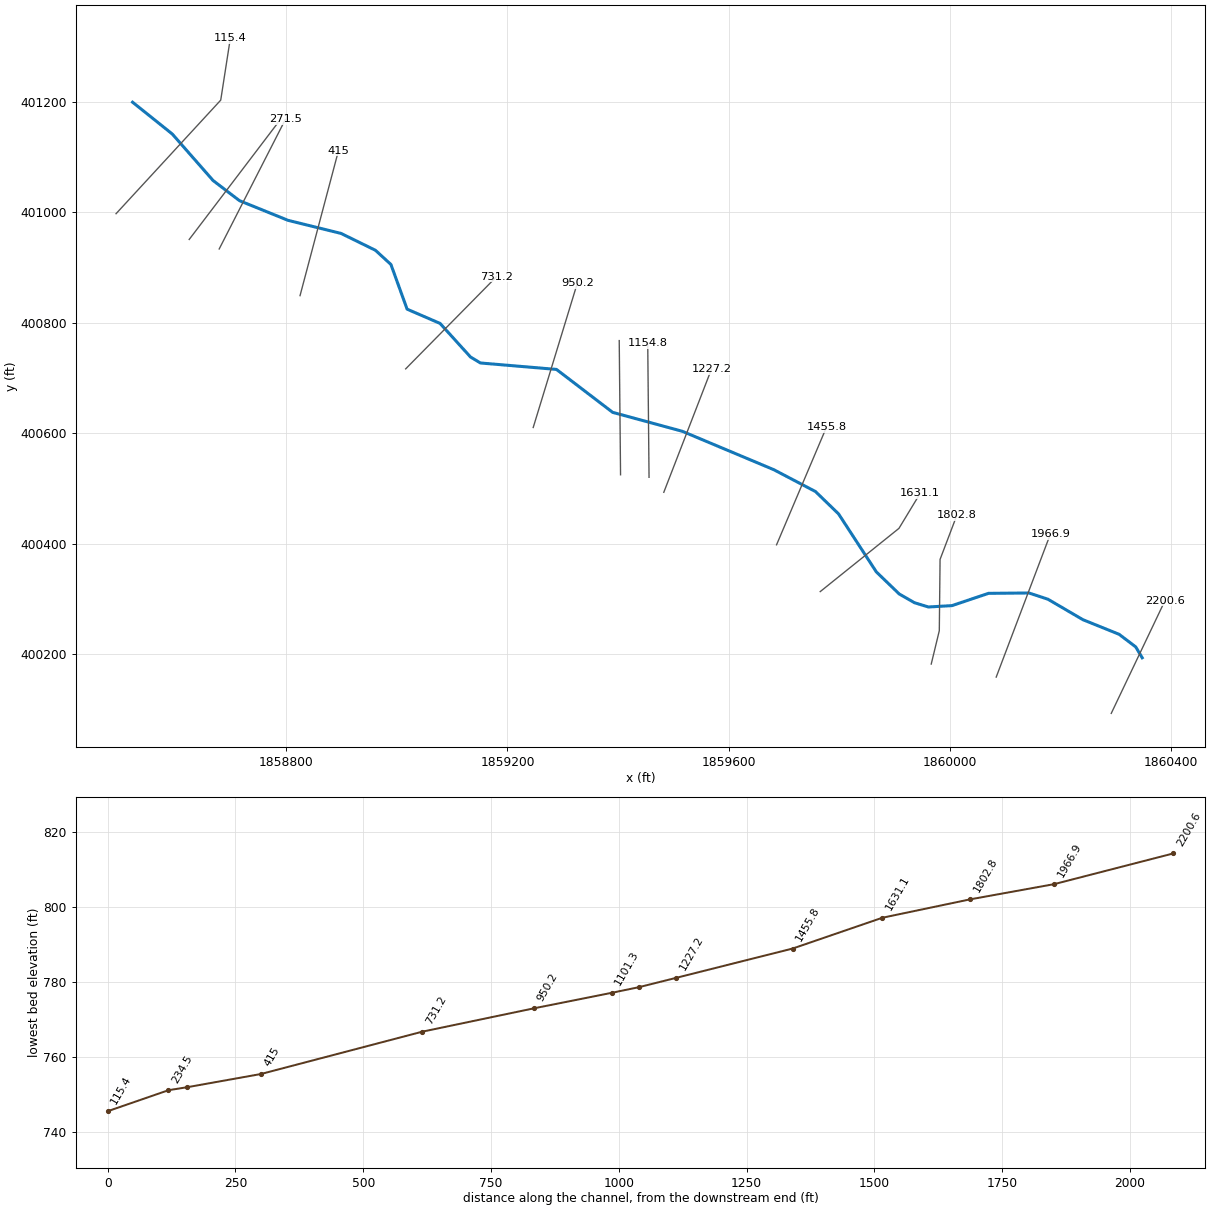
--- ASHBRANCH.prj (project) ---

Proj Title=ASHBRANCH
Current Plan=p01
Default Exp/Contr=0,0
English Units
Geom File=g01
Flow File=f01
Plan File=p01
BEGIN DESCRIPTION:
END DESCRIPTION:
DSS Export Rating Curves= 0
DSS Export Rating Curve Sorted= 0
DSS Export Volume Flow Curves= 0
DXF OffsetX= 0
DXF OffsetY= 0
DXF ScaleX= 0
DXF ScaleY= 0

--- ASHBRANCH.p01 (plan) ---

Plan Title=Floodplain
Program Version=4.00
Geom File=g01
Flow File=f01
K Sum by GR=0
Std Step Tol=0.01
Critical Tol=0.01
Num of Std Step Trials=20
Max Error Tol=0.3
Flow Tol Ratio=0.001
Split Flow NTrial=30
Split Flow Tol=0.02
Split Flow Ratio=0.02
Log Output Level=0
Friction Slope Method=1
Unsteady Friction Slope Method=2
Unsteady Bridges Friction Slope Method=1
Global Log Level=0
CheckData=False
Run HTab=0
Run UNet=0
Run PostProcess=0
UNET Theta=0
UNET Theta Warmup=0
UNET ZTol=0
UNET ZSATol=0
UNET MxIter=0
UNET MaxInSteps=0
UNET DtIC=0
UNET DtMin=0
UNET MaxCRTS=0
UNET WFStab=0
UNET SFStab=0
UNET WFX=0
UNET SFX=0
UNET DSS MLevel=0
UNET DZMax Abort=0
UNET Convert EG Bridges=0
UNET Use Existing IB Tables=0
UNET Froude Limit=0
UNET Froude Power=0
Write IC File=0
Echo Input=False
Echo Output=False
Write Detailed=0

--- ASHBRANCH.f01 (steady flow) ---

Flow Title=NFF Regression Equation
Program Version=4.10
Number of Profiles= 1
Profile Names=P100yr
River Rch & RM=ASHBRANCH,Main            ,2200.6
1007.567
River Rch & RM=ASHBRANCH,Main            ,415
1045.517
Boundary for River Rch & Prof#=ASHBRANCH,Main            , 1
Up Type= 0
Dn Type= 3
Dn Slope=0.03
DSS Import GetInterval= 0
DSS Import GetPeak= 0
DSS Import FillOption= 0

--- ASHBRANCH.g01 (geometry) ---

Geom Title=USGS 10m DEM
Program Version=4.10

River Reach=ASHBRANCH       ,Main
Reach XY= 30
     1860347.642      400192.947     1860335.793      400212.756
     1860305.793      400235.534     1860240.515      400261.923
      1860177.15      400299.049     1860142.919      400310.357
     1860069.681        400309.7     1860003.848      400287.478
      1859961.07      400284.978     1859935.793      400292.756
     1859908.293      400308.589     1859866.904      400348.589
     1859798.618      400453.677     1859756.904      400494.145
      1859681.57      400533.728     1859516.154      400603.311
     1859390.296      400637.596     1859288.654      400715.395
     1859151.154      400727.061     1859133.237      400737.895
     1859078.237      400798.728     1859018.654      400824.561
     1858989.387      400905.511     1858961.431      400931.228
     1858899.209      400961.784     1858803.372      400985.482
     1858715.698      401021.072     1858667.955       401057.53
     1858594.209      401141.784     1858522.303      401199.544

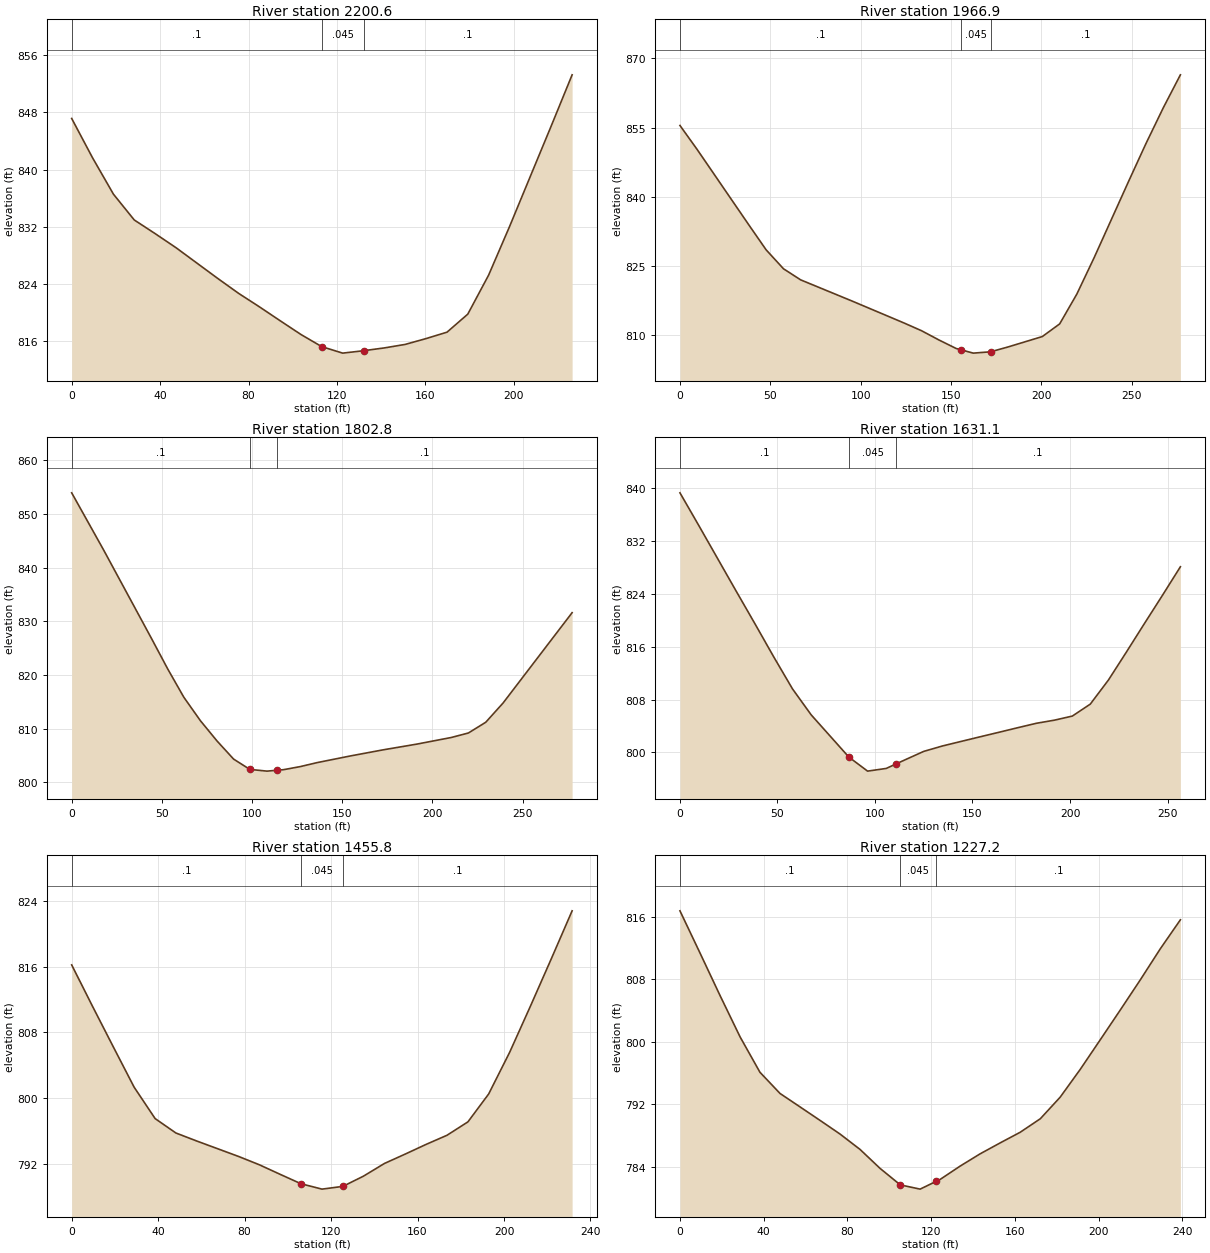
Type RM Length L Ch R = 1 ,2200.6  ,233.4,233.6,233.7
XS GIS Cut Line= 2
     1860291.643      400092.242     1860388.865      400296.687
#Sta/Elev= 27
       0  847.15     9.4  841.67    18.9  836.56    28.3  832.96    37.7  831.06
    47.2  829.08    56.6  826.94      66   824.8    75.5   822.7    84.9  820.82
    94.3  818.87   103.8  816.93   112.4  815.38   113.2  815.24   122.6  814.34
   127.4  814.51   132.1  814.68   141.5  815.07   150.9  815.56   160.4  816.38
   169.8  817.27   179.2  819.79   188.6  825.23   198.1  832.04   207.5  839.06
     217  846.14   226.4  853.25
#Mann= 3 , 0 , 0
       0      .1       0   113.2    .045       0   132.1      .1       0
Bank Sta=113.2,132.1
XS Rating Curve= 0 ,0
Exp/Cntr=0.3,0.1

Type RM Length L Ch R = 1 ,1966.9  ,155.9,164.1,171.9
XS GIS Cut Line= 2
     1860083.652      400157.955     1860181.569      400416.983
#Sta/Elev= 23
       0  855.45     9.6   850.2    38.2  833.86    47.7   828.5    57.3   824.4
    66.8     822    95.5  817.37   124.1  812.64   133.7  810.98   143.2     809
   152.8  807.14   155.7  806.83   162.3  806.13   171.9  806.42   181.4  807.45
   200.5  809.72   210.1  812.46   219.6  818.92   229.2  826.83   248.3  843.39
   257.8  851.49   267.4  859.25   276.9  866.42
#Mann= 3 , 0 , 0
       0      .1       0   155.7    .045       0   171.9      .1       0
Bank Sta=155.7,171.9
XS Rating Curve= 0 ,0
Exp/Cntr=0.3,0.1

Type RM Length L Ch R = 1 ,1802.8  ,191.8,171.8,151.8
XS GIS Cut Line= 4
     1859966.198       400181.61     1859980.781      400242.027
      1859982.17      400371.194     1860012.725      400451.749
#Sta/Elev= 22
       0  853.96    17.8  843.25    44.4  826.72    53.3   821.1    62.2  815.85
    71.4  811.47    80.6   807.7    89.8  804.32    98.8   802.4   108.3  802.08
   113.8  802.24   117.5  802.35   126.7  802.92     136  803.66   154.4   804.9
   172.9  806.06   191.3  807.11   210.5  808.35     220  809.19   229.6  811.19
   239.2  814.77   277.5  831.62
#Mann= 3 , 0 , 0
       0      .1       0    98.8    .045       0   113.8      .1       0
Bank Sta=98.8,113.8
XS Rating Curve= 0 ,0
Exp/Cntr=0.3,0.1

Type RM Length L Ch R = 1 ,1631.1  ,164,175.3,186.2
XS GIS Cut Line= 3
     1859765.503       400312.86     1859907.864      400427.444
     1859946.059      400490.638
#Sta/Elev= 30
       0  839.33     9.6  834.41    19.2  829.43    28.8  824.45    38.5  819.47
    48.1  814.47    57.7  809.63    67.3  805.69      77  802.48    86.6   799.3
    95.8  797.26    96.2  797.17   105.8  797.58   110.8  798.26   115.4  798.88
     125  800.16   134.6  800.98   144.3  801.68   153.9  802.37   163.5  803.05
   173.1  803.74   182.8  804.42     192  804.89   201.2  805.51   210.4  807.32
   219.7  810.97   228.9   815.2   238.1   819.5   247.4   823.8   256.6  828.13
#Mann= 3 , 0 , 0
       0      .1       0    86.6    .045       0   110.8      .1       0
Bank Sta=86.6,110.8
XS Rating Curve= 0 ,0
Exp/Cntr=0.3,0.1

Type RM Length L Ch R = 1 ,1455.8  ,228,228.7,229.4
XS GIS Cut Line= 2
     1859686.569      400397.678     1859776.847      400610.872
#Sta/Elev= 27
       0   816.2     9.6  811.19    19.3  806.22    28.9  801.34    38.6  797.53
    48.2  795.78    57.9   794.8    67.5  793.87    77.2  792.93    86.8  791.92
    96.5  790.75   106.1  789.61   111.2  789.27   115.8  788.96   125.4  789.29
   126.2  789.39     135  790.54   144.7  792.08   154.4  793.23     164   794.4
   173.6   795.5   183.3  797.13   192.9  800.52   202.6  805.58   212.2  811.18
   221.9  816.96   231.5  822.77
#Mann= 3 , 0 , 0
       0      .1       0   106.1    .045       0   125.4      .1       0
Bank Sta=106.1,125.4
XS Rating Curve= 0 ,0
Exp/Cntr=0.3,0.1

Type RM Length L Ch R = 1 ,1227.2  ,63.8,72.3,81.3
XS GIS Cut Line= 2
     1859482.715      400492.782     1859568.826      400715.698
#Sta/Elev= 28
       0  816.78     9.6  811.36    19.1  805.95    28.7  800.63    38.2  796.09
    47.8  793.37    57.4  791.64    66.9  789.92    76.5  788.16      86   786.2
    95.6  783.76   105.2  781.66   107.4  781.53   114.7  781.11   122.4  782.11
   124.3  782.36   133.8  784.06   143.4  785.64   152.9  787.03   162.5   788.4
   172.1  790.13   181.6   792.9   191.2  796.47   200.7  800.24   210.3  804.07
   219.8  807.91   229.4  811.91     239  815.63
#Mann= 3 , 0 , 0
       0      .1       0   105.2    .045       0   122.4      .1       0
Bank Sta=105.2,122.4
XS Rating Curve= 0 ,0
Exp/Cntr=0.3,0.1

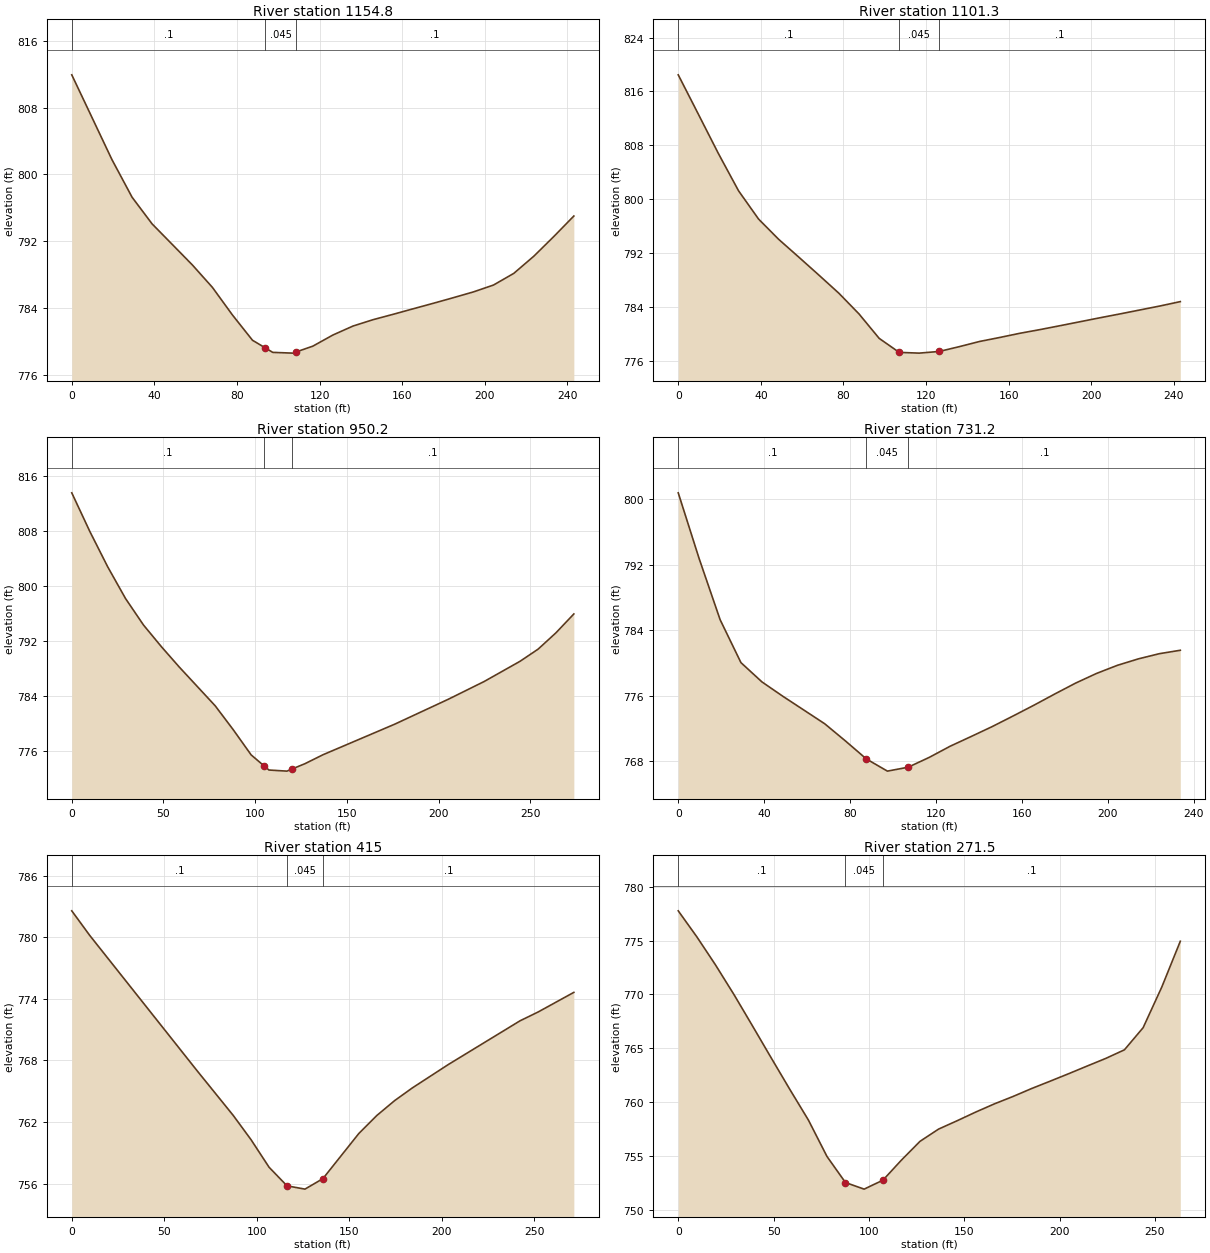
Type RM Length L Ch R = 1 ,1154.8  ,53.3,53.5,53.1
XS GIS Cut Line= 2
     1859456.033      400519.942     1859453.651      400763.074
#Sta/Elev= 28
       0  811.91     9.7  806.86    19.4   801.8    29.2  797.28    38.9  794.09
    48.6  791.65    58.4  789.18    68.1   786.5    77.8   783.2    87.5  780.18
    93.6  779.28    97.3  778.73     107  778.64   108.6  778.78   116.7  779.47
   126.4   780.8   136.2  781.88   145.9  782.64   155.6  783.28   165.3  783.94
   175.1   784.6   184.8  785.27   194.5  785.96   204.2  786.78     214  788.17
   223.7  790.22   233.4  792.58   243.1  795.03
#Mann= 3 , 0 , 0
       0      .1       0    93.6    .045       0   108.6      .1       0
Bank Sta=93.6,108.6
XS Rating Curve= 0 ,0
Exp/Cntr=0.3,0.1

Type RM Length L Ch R = 1 ,1101.3  ,158,151.1,144
XS GIS Cut Line= 2
     1859404.519       400524.49     1859402.137      400767.622
#Sta/Elev= 28
       0  818.46     9.7  812.64    19.4   806.8    29.2  801.24    38.9  797.04
    48.6  794.04    58.4  791.38    68.1  788.72    77.8  786.02    87.5  782.96
    97.3  779.32   102.8  778.14     107  777.24   116.7  777.13   117.8  777.16
   126.4  777.38   136.2   778.1   145.9  778.86   155.6  779.45   165.3  780.07
   175.1  780.62   184.8   781.2   194.5  781.79   204.2  782.38     214  782.96
   223.7  783.55   233.4  784.14   243.1  784.78
#Mann= 3 , 0 , 0
       0      .1       0     107    .045       0   126.4      .1       0
Bank Sta=107,126.4
XS Rating Curve= 0 ,0
Exp/Cntr=0.3,0.1

Type RM Length L Ch R = 1 ,950.2   ,229.8,219.1,208
XS GIS Cut Line= 2
     1859246.604      400610.143     1859326.465      400871.948
#Sta/Elev= 23
       0  813.55     9.8  807.95    19.6  802.77    29.3  798.16    39.1   794.3
    48.9  791.13    58.6  788.18    78.2  782.53      88  779.06    97.8  775.38
   104.8  773.79   107.5  773.18   117.3  773.02   119.8   773.3   127.1   774.1
   136.9   775.4     176  779.85   205.3  783.49   224.8  786.07   244.4  789.02
   254.2  790.78   263.9  793.15   273.7  795.91
#Mann= 3 , 0 , 0
       0      .1       0   104.8    .045       0   119.8      .1       0
Bank Sta=104.8,119.8
XS Rating Curve= 0 ,0
Exp/Cntr=0.3,0.1

Type RM Length L Ch R = 1 ,731.2   ,304.1,316.1,327.8
XS GIS Cut Line= 2
     1859016.048      400716.393     1859179.937       400883.06
#Sta/Elev= 27
       0  800.78     9.7  792.77    19.5  785.28    29.2  780.03      39  777.67
    48.7  775.92    58.4  774.25    68.2  772.56    77.9  770.45    87.6  768.26
    94.7  767.18    97.4  766.77   107.1  767.25   109.7  767.57   116.9  768.45
   126.6  769.81   136.4     771   146.1   772.2   155.8  773.49   165.6  774.82
   175.3  776.19     185  777.52   194.8  778.71   204.5   779.7   214.3  780.49
     224  781.12   233.8  781.54
#Mann= 3 , 0 , 0
       0      .1       0    87.6    .045       0   107.1      .1       0
Bank Sta=87.6,107.1
XS Rating Curve= 0 ,0
Exp/Cntr=0.3,0.1

Type RM Length L Ch R = 1 ,415     ,148.3,143.5,138.7
XS GIS Cut Line= 2
     1858825.076      400849.032     1858894.521      401111.532
#Sta/Elev= 17
       0  782.56     9.7  780.17    67.9  766.96    87.3  762.64      97  760.26
   106.7  757.59   116.4  755.78   126.1  755.46   135.8  756.48   155.2  760.87
   164.9  762.62   174.6  764.08   184.2  765.32   203.6  767.59   242.4  771.85
   252.1   772.7   271.5  774.62
#Mann= 3 , 0 , 0
       0      .1       0   116.4    .045       0   135.8      .1       0
Bank Sta=116.4,135.8
XS Rating Curve= 0 ,0
Exp/Cntr=0.3,0.1

Type RM Length L Ch R = 1 ,271.5   ,41.1,37,33
XS GIS Cut Line= 2
      1858678.93      400933.615     1858798.514      401168.198
#Sta/Elev= 29
       0  777.75     9.8  775.33    19.5  772.75    29.3  769.97      39  767.07
    48.8  764.11    58.5  761.21    68.3  758.35      78  754.99    87.7  752.57
    97.5  751.96   102.7   752.4   107.3  752.78     117  754.64   126.8  756.39
   136.5  757.52   146.3   758.3     156   759.1   165.8  759.86   175.5  760.54
   185.3  761.28     195  761.96   204.8  762.66   214.5  763.37   224.3  764.08
     234  764.87   243.8  766.92   253.6  770.69   263.3  774.93
#Mann= 3 , 0 , 0
       0      .1       0    87.7    .045       0   107.3      .1       0
Bank Sta=87.7,107.3
XS Rating Curve= 0 ,0
Exp/Cntr=0.3,0.1

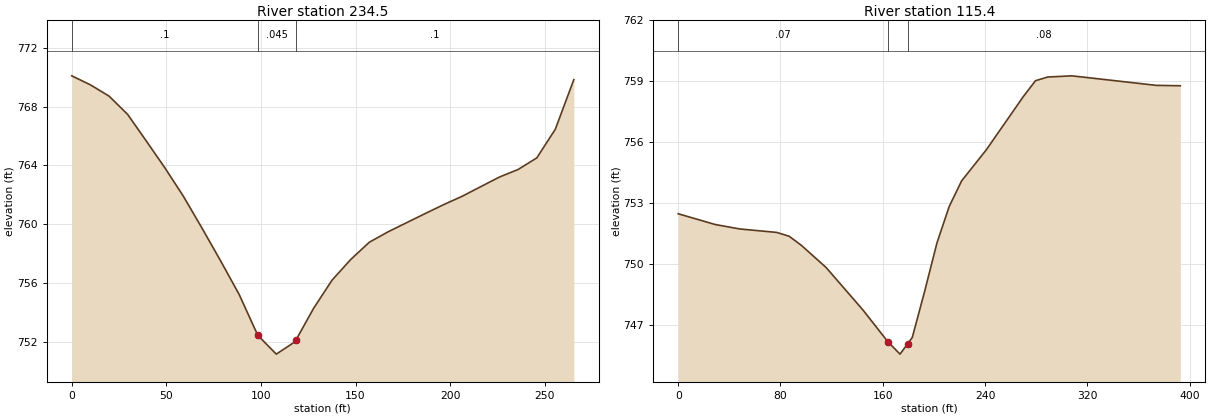
Type RM Length L Ch R = 1 ,234.5   ,121.2,119,116.9
XS GIS Cut Line= 2
     1858624.695      400950.838     1858785.112      401162.296
#Sta/Elev= 30
       0   770.1     9.8  769.49    19.7  768.72    29.5  767.48    39.3  765.68
    49.2  763.84      59   761.9    68.8  759.74    78.6  757.52    88.5  755.21
    98.3  752.44   103.6  751.74   108.1  751.15     118  751.99   118.6  752.13
   127.8  754.26   137.6  756.19   147.5   757.6   157.3  758.77   167.1  759.47
     177   760.1   186.8  760.72   196.6  761.33   206.4   761.9   216.3  762.56
   226.1  763.21   235.9  763.72   245.8  764.51   255.6  766.46   265.4  769.84
#Mann= 3 , 0 , 0
       0      .1       0    98.3    .045       0   118.6      .1       0
Bank Sta=98.3,118.6
XS Rating Curve= 0 ,0
Exp/Cntr=0.3,0.1

Type RM Length L Ch R = 1 ,115.4   ,111.4,115.4,119.2
XS GIS Cut Line= 3
     1858492.452      400997.512     1858681.688      401203.241
      1858699.05       401315.22
#Sta/Elev= 23
       0  752.46    28.9  751.93    48.2  751.71    77.1  751.54    86.8  751.35
    96.4   750.9   115.7  749.81   144.6  747.71   163.9  746.16   173.5  745.54
   179.6  746.06   183.1  746.36   192.8  748.64   202.4  751.02     212  752.82
   221.7  754.08     241  755.61   269.9  758.23   279.5  759.02     289   759.2
   307.9  759.26     374  758.79   392.8  758.77
#Mann= 3 , 0 , 0
       0     .07       0   163.9    .045       0   179.6     .08       0
Bank Sta=163.9,179.6
XS Rating Curve= 0 ,0
Exp/Cntr=0.3,0.1

Chan Stop Cuts=-1
Use User Specified Reach Order=0
Composite Channel Slope=5